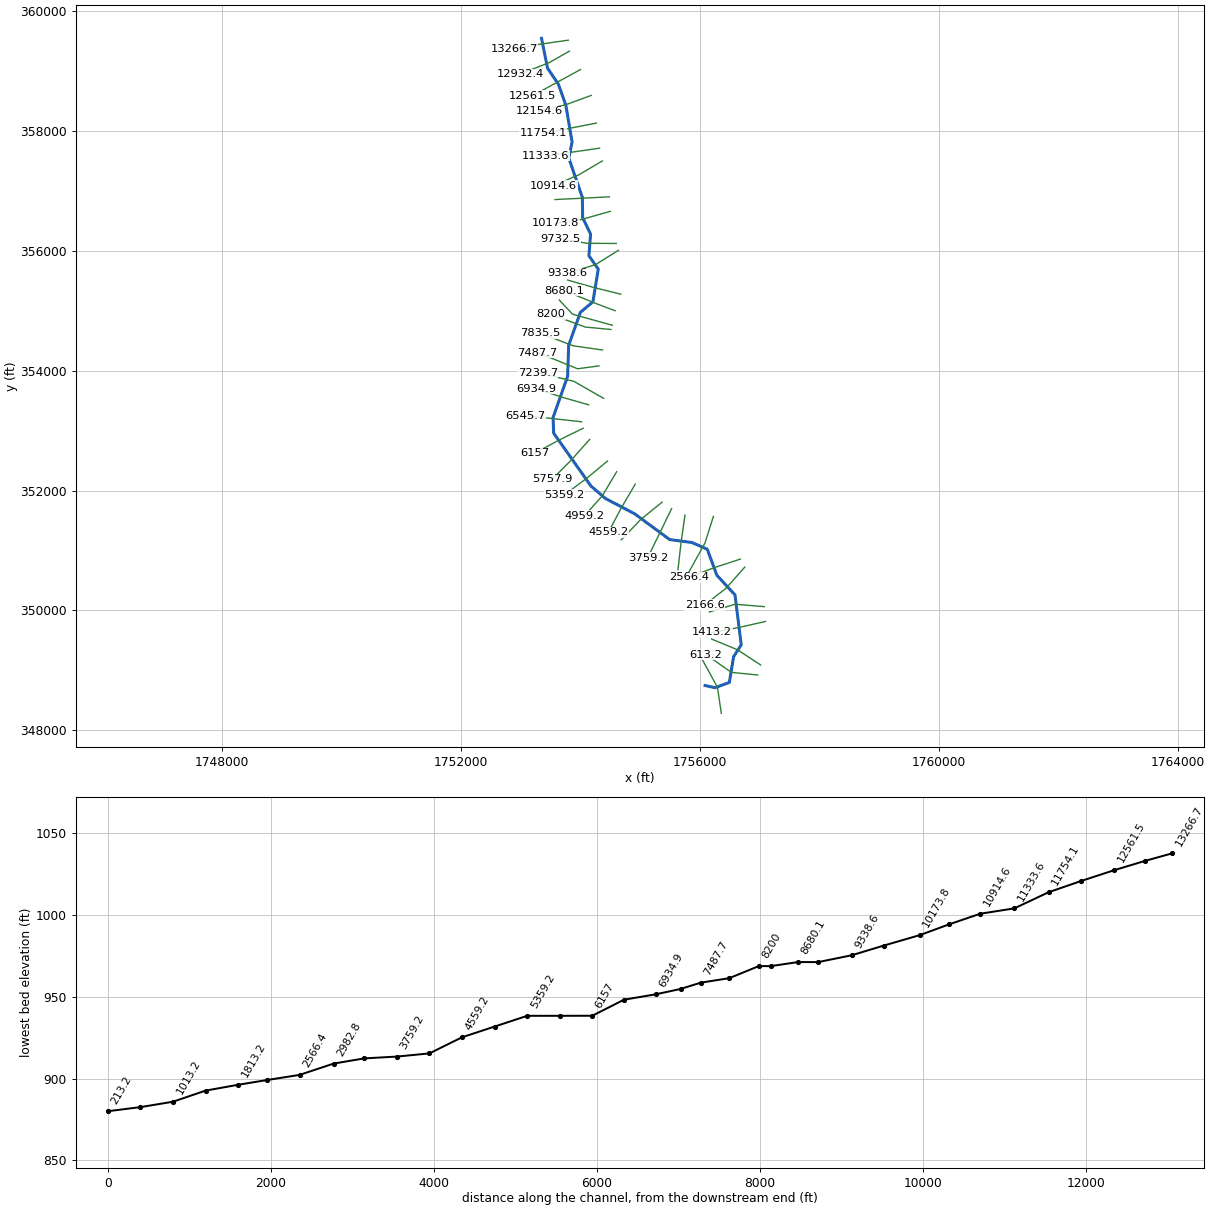
--- HlnsRn.prj (project) ---

Proj Title=HlnsRn
Current Plan=p01
Default Exp/Contr=0,0
English Units
Geom File=g01
Flow File=f01
Plan File=p01
BEGIN DESCRIPTION:
END DESCRIPTION:
DSS Export Rating Curves= 0
DSS Export Rating Curve Sorted= 0
DSS Export Volume Flow Curves= 0
DXF OffsetX= 0
DXF OffsetY= 0
DXF ScaleX= 0
DXF ScaleY= 0

--- HlnsRn.p01 (plan) ---

Plan Title=Floodplain
Program Version=4.00
Geom File=g01
Flow File=f01
K Sum by GR=0
Std Step Tol=0.01
Critical Tol=0.01
Num of Std Step Trials=20
Max Error Tol=0.3
Flow Tol Ratio=0.001
Split Flow NTrial=30
Split Flow Tol=0.02
Split Flow Ratio=0.02
Log Output Level=0
Friction Slope Method=1
Unsteady Friction Slope Method=2
Unsteady Bridges Friction Slope Method=1
Global Log Level=0
CheckData=False
Run HTab=0
Run UNet=0
Run PostProcess=0
UNET Theta=0
UNET Theta Warmup=0
UNET ZTol=0
UNET ZSATol=0
UNET MxIter=0
UNET MaxInSteps=0
UNET DtIC=0
UNET DtMin=0
UNET MaxCRTS=0
UNET WFStab=0
UNET SFStab=0
UNET WFX=0
UNET SFX=0
UNET DSS MLevel=0
UNET DZMax Abort=0
UNET Convert EG Bridges=0
UNET Use Existing IB Tables=0
UNET Froude Limit=0
UNET Froude Power=0
Write IC File=0
Echo Input=False
Echo Output=False
Write Detailed=0

--- HlnsRn.f01 (steady flow) ---

Flow Title=NFF Regression Equation
Program Version=4.00
Number of Profiles= 1
Profile Names=P100yr
River Rch & RM=HlnsRn,Main            ,13266.7
772.2763
River Rch & RM=HlnsRn,Main            ,12154.6
788.5428
River Rch & RM=HlnsRn,Main            ,11754.1
1020.309
River Rch & RM=HlnsRn,Main            ,7487.7
1128.186
River Rch & RM=HlnsRn,Main            ,7487.7
1361.726
River Rch & RM=HlnsRn,Main            ,2982.8
1504.018
River Rch & RM=HlnsRn,Main            ,2566.4
1733.737
River Rch & RM=HlnsRn,Main            ,213.2
1789.681
Boundary for River Rch & Prof#=HlnsRn,Main            , 1
Up Type= 0
Dn Type= 3
Dn Slope=0.011734
DSS Import GetInterval= 0
DSS Import GetPeak= 0
DSS Import FillOption= 0

--- HlnsRn.g01 (geometry) ---

Geom Title=USGS 3m DEM
Program Version=4.00

River Reach=HlnsRn          ,Main
Reach XY= 30
     1753352.441      359550.214     1753452.378      359052.789
     1753634.183      358784.598     1753758.269        358434.9
     1753863.234      357820.697     1753808.181      357550.436
      1754034.65      356896.055     1754040.387       356555.56
     1754172.765      356282.122     1754144.554      355919.709
     1754300.992      355697.854     1754211.828       355151.48
     1754001.324      354973.528     1753806.012      354424.483
     1753788.651       353907.99     1753545.428      353220.008
     1753555.437      352957.254     1754179.276      352074.223
     1754422.331      351865.889     1754908.442      351611.983
      1755496.55      351180.126     1755865.474      351132.383
      1756123.72      351019.535     1756285.045      350584.712
      1756588.13      350255.647      1756692.21      349422.385
     1756564.696      349224.879     1756493.321      348795.298
     1756253.677      348707.054     1756086.807      348743.692

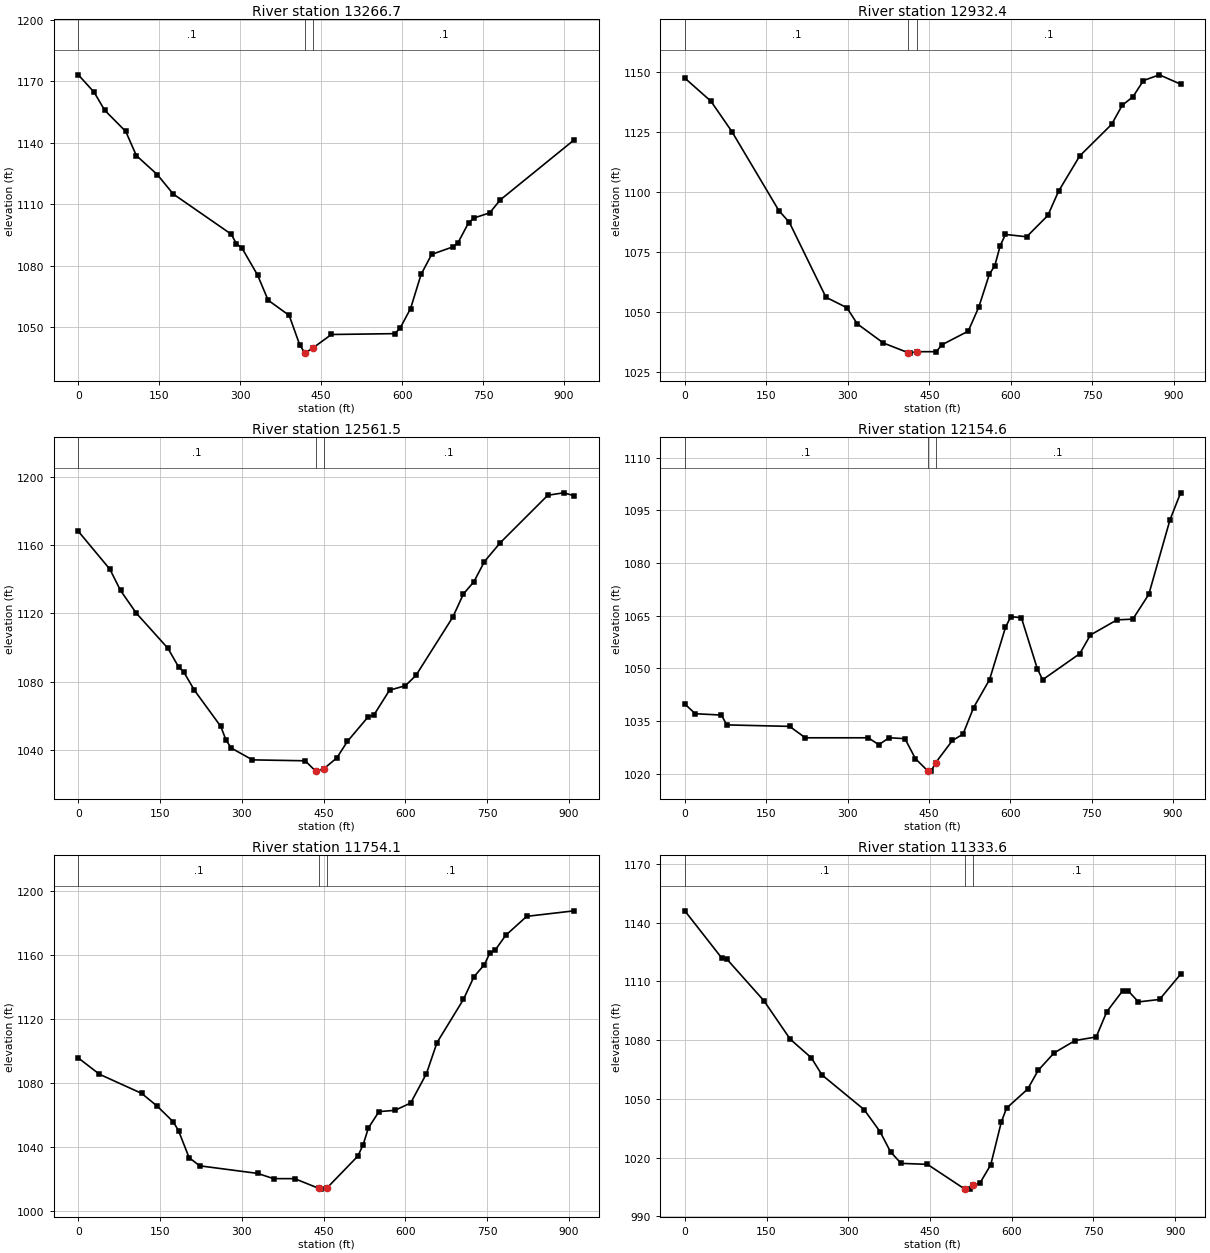
Type RM Length L Ch R = 1 ,13266.7 ,328.647,334.336,340.025
XS GIS Cut Line= 3
     1753799.997      359519.575      1753306.82      359449.121
     1752892.905      359374.264
#Sta/Elev= 30
       0 1173.22    29.3 1164.71    48.8 1155.96    87.9  1145.6   107.5 1133.85
   146.5 1124.52   175.8 1115.11   283.3 1095.51     293 1090.79   302.8 1088.93
   332.1 1075.58   351.7 1063.31   390.7  1055.9   410.3 1041.49   419.3 1037.78
     420  1037.5   434.3 1039.93   468.9 1046.59   586.2    1047     596 1049.57
   615.6 1059.18   635.1 1075.88   654.7 1085.64   693.8 1089.29   703.6 1091.37
   723.2 1101.07     733  1103.4   762.3  1105.9   781.9 1112.24   918.8  1141.5
#Mann= 3 , 0 , 0
       0      .1       0   419.3    .045       0   434.3      .1       0
Bank Sta=419.3,434.3
XS Rating Curve= 0 ,0
Exp/Cntr=0.3,0.1

Type RM Length L Ch R = 1 ,12932.4 ,368.273,370.855,373.436
XS GIS Cut Line= 3
     1753818.825      359336.398     1753484.178       359146.61
     1752993.426      358953.001
#Sta/Elev= 30
       0 1147.35    48.1 1137.71    86.6 1125.09   173.1 1092.17   192.4 1087.27
   259.7 1056.13   298.2 1051.77   317.4 1045.03   365.5 1037.06   411.4    1033
     414 1032.86   426.4 1033.46   462.9 1033.46   472.6 1036.28   521.5 1042.01
     541 1052.06   560.6 1065.84   570.3 1069.15   580.1 1077.42   589.9 1082.27
     629 1081.29     668 1090.17   687.6 1100.21   726.7 1114.95   785.3 1128.07
   804.8 1136.02   824.4 1139.51   843.9 1146.32   873.2  1148.7   912.3 1144.82
#Mann= 3 , 0 , 0
       0      .1       0   411.4    .045       0   426.4      .1       0
Bank Sta=411.4,426.4
XS Rating Curve= 0 ,0
Exp/Cntr=0.3,0.1

Type RM Length L Ch R = 1 ,12561.5 ,410.374,406.941,401.011
XS GIS Cut Line= 3
     1754003.965      359029.047     1753604.523      358811.169
      1753205.08      358593.291
#Sta/Elev= 30
       0 1168.31    58.1 1145.93    77.4 1133.53   106.5 1120.15   164.6 1099.46
   183.9 1088.59   193.6 1085.55     213 1074.86   261.4  1053.6   271.1 1045.51
   280.7 1040.86   319.5 1033.92   416.3 1033.38   435.6  1027.3   450.6 1028.71
   474.4 1035.08   493.7 1044.73   532.4 1059.41   542.1 1060.13   571.2 1074.89
   600.2 1077.53   619.6 1083.57   687.3 1117.86   706.7 1131.44   726.1 1138.72
   745.4 1150.56   774.5 1161.64   861.6 1189.51   890.6 1190.94     910 1189.24
#Mann= 3 , 0 , 0
       0      .1       0   435.6    .045       0   450.6      .1       0
Bank Sta=435.6,450.6
XS Rating Curve= 0 ,0
Exp/Cntr=0.3,0.1

Type RM Length L Ch R = 1 ,12154.6 ,404.038,400.51,399.478
XS GIS Cut Line= 3
     1754182.538      358596.582     1753755.828      358441.167
     1753309.011      358332.337
#Sta/Elev= 30
       0 1039.81    19.3 1037.04    67.6 1036.65    77.3 1033.85   193.2 1033.43
   222.2 1030.18   338.2 1030.18   357.5 1028.22   376.8 1030.18   405.8 1029.94
   425.1 1024.23   447.6 1020.79   454.1 1020.68   462.6 1023.11   493.3 1029.41
   512.8  1031.2   532.4  1038.8   561.8 1046.76   591.1 1061.61   600.9 1064.71
   620.5 1064.38   649.8 1049.87   659.6 1046.72   728.1 1054.15   747.7 1059.46
   796.6 1063.78   825.9 1063.99   855.3 1071.04   894.4 1092.29     914 1099.98
#Mann= 3 , 0 , 0
       0      .1       0   447.6    .045       0   462.6      .1       0
Bank Sta=447.6,462.6
XS Rating Curve= 0 ,0
Exp/Cntr=0.3,0.1

Type RM Length L Ch R = 1 ,11754.1 ,421.673,420.435,419.198
XS GIS Cut Line= 3
     1754269.558      358134.983     1753822.923      358048.137
     1753376.288      357961.292
#Sta/Elev= 30
       0 1095.72    38.7 1085.57   116.2  1073.6   145.2 1065.49   174.3 1055.79
   183.9 1050.27   203.3 1033.44   222.7 1028.34   329.1  1023.6   358.2 1020.34
   396.9 1020.34   441.7 1014.21   445.3 1013.78   456.7 1014.63   513.1 1034.45
   522.8 1041.63   532.4 1052.04   551.8 1062.22   580.9 1062.99   609.9 1067.57
   638.9 1085.95   658.3 1105.35   706.7 1132.26   726.1 1146.46   745.4 1154.12
   755.1 1161.26   764.8 1162.98   784.1 1172.25   822.9 1184.21     910 1187.66
#Mann= 3 , 0 , 0
       0      .1       0   441.7    .045       0   456.7      .1       0
Bank Sta=441.7,456.7
XS Rating Curve= 0 ,0
Exp/Cntr=0.3,0.1

Type RM Length L Ch R = 1 ,11333.6 ,413.043,419.063,425.083
XS GIS Cut Line= 3
     1754322.238      357716.148     1753871.856       357651.49
     1753421.473      357586.831
#Sta/Elev= 30
       0 1146.03    67.8 1121.94    77.4 1121.31   145.2 1100.12   193.6 1080.45
   232.3 1070.96   251.7 1062.25   329.1 1044.53   358.2 1033.33   377.6 1022.98
   396.9 1017.08   445.3 1016.58   513.8 1003.96   522.8 1003.93   528.8 1005.86
   542.1 1007.22   561.5 1016.35   580.9 1038.18   590.5 1045.27   629.3 1055.02
   648.6 1064.58   677.7 1073.46   716.4 1079.81   755.1 1081.64   774.5 1094.53
   803.5 1105.16   813.2 1105.33   832.6 1099.52   871.3 1100.78     910 1113.66
#Mann= 3 , 0 , 0
       0      .1       0   513.8    .045       0   528.8      .1       0
Bank Sta=513.8,528.8
XS Rating Curve= 0 ,0
Exp/Cntr=0.3,0.1

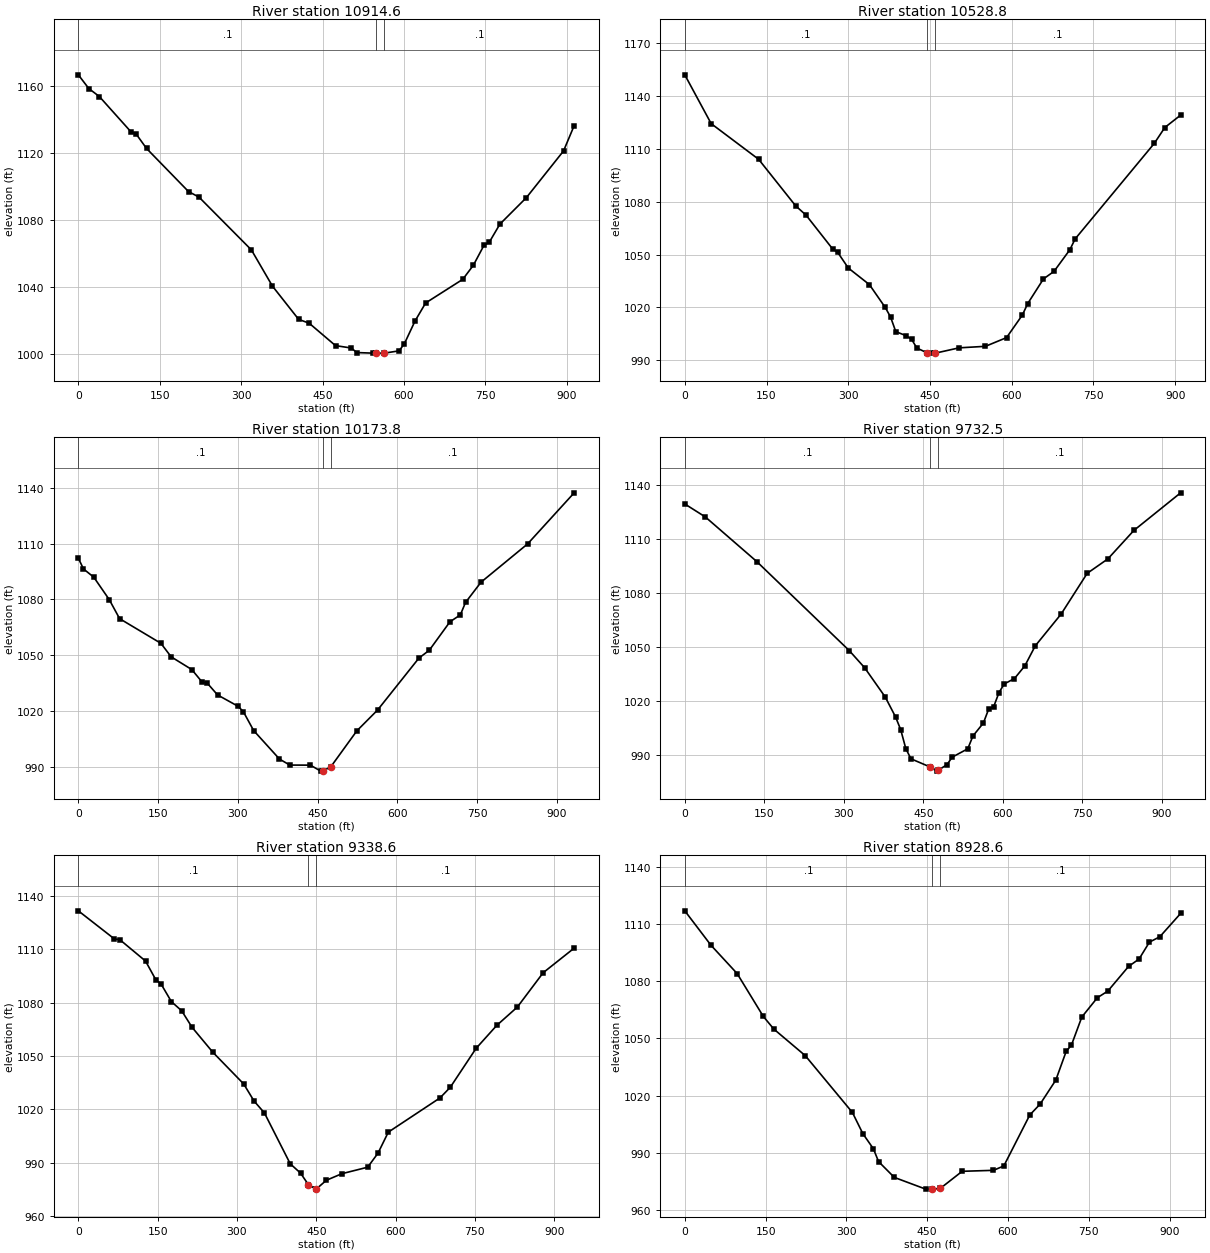
Type RM Length L Ch R = 1 ,10914.6 ,394.044,385.783,377.522
XS GIS Cut Line= 3
     1754367.976      357501.848     1753976.087      357272.121
     1753554.465      357090.197
#Sta/Elev= 30
       0 1166.68    19.3  1158.5    38.7 1153.74    96.7 1132.77   106.3 1131.46
   125.6 1122.78     203 1097.03   222.3 1093.73   318.9 1062.21   357.6 1040.64
   405.9 1020.79   425.3  1018.5   473.8 1005.13   503.1 1003.69   512.9 1000.98
   542.2 1000.65   548.9 1000.65   563.9 1000.65     591 1002.01   600.8 1006.32
   620.4 1019.86   639.9 1030.58   708.3 1044.68   727.8 1053.08   747.4    1065
   757.1 1066.81   776.7 1077.61   825.5 1093.42   893.9 1121.25   913.5 1136.36
#Mann= 3 , 0 , 0
       0      .1       0   548.9    .045       0   563.9      .1       0
Bank Sta=548.9,563.9
XS Rating Curve= 0 ,0
Exp/Cntr=0.3,0.1

Type RM Length L Ch R = 1 ,10528.8 ,349.738,354.988,360.239
XS GIS Cut Line= 3
     1754486.511      356903.224     1754032.067      356880.727
     1753577.624       356858.23
#Sta/Elev= 30
       0 1151.97    48.4 1124.28   135.5 1104.05   203.3  1077.7   222.7 1072.31
   271.1 1053.27   280.7 1051.22   300.1 1042.37   338.8 1032.96   367.9 1019.99
   377.6 1014.62   387.2  1006.3   406.6 1003.93   416.3 1001.88     426  996.95
     445  994.23     455  994.09     460  994.09   503.4  997.09   551.8  997.95
   590.5 1002.89   619.6 1015.73   629.3 1022.17   658.3 1036.21   677.7 1040.49
   706.7 1052.73   716.4 1058.88   861.6 1113.05     881 1122.08     910 1129.11
#Mann= 3 , 0 , 0
       0      .1       0     445    .045       0     460      .1       0
Bank Sta=445,460
XS Rating Curve= 0 ,0
Exp/Cntr=0.3,0.1

Type RM Length L Ch R = 1 ,10173.8 ,447.928,441.273,433.347
XS GIS Cut Line= 3
     1754501.176      356661.243     1753997.412      356518.166
     1753593.039      356459.241
#Sta/Elev= 30
       0 1102.16     9.7 1096.37    29.1 1091.94    58.2 1079.85    77.6 1069.64
   155.2 1056.38   174.6 1049.08   213.4 1042.23   232.8 1035.49   242.4 1034.94
   261.8 1028.59   300.6 1022.45   310.3 1019.56   329.7 1009.41   378.2  994.09
   397.6  990.85   436.4  990.81   455.8  987.59   459.6  987.69   474.6  989.86
   523.7 1009.27   562.6 1020.44   640.4 1048.41   659.9 1052.63   698.8 1067.96
   718.3 1071.65     728 1078.34   757.2 1089.26   844.8 1109.86   932.3 1137.34
#Mann= 3 , 0 , 0
       0      .1       0   459.6    .045       0   474.6      .1       0
Bank Sta=459.6,474.6
XS Rating Curve= 0 ,0
Exp/Cntr=0.3,0.1

Type RM Length L Ch R = 1 ,9732.5  ,380.944,393.923,403.832
XS GIS Cut Line= 3
       1754602.8      356125.037     1754117.884      356127.387
     1753673.303       356200.49
#Sta/Elev= 30
       0 1129.63    38.8  1122.4   135.8 1097.63   310.3 1048.16   339.4 1038.61
   378.2 1022.37   397.6 1011.35   407.3 1004.29     417  993.71   426.7  988.06
   462.8  983.52   475.2  981.21   477.8  981.62   494.7  984.82   504.5  988.97
   533.9  993.62   543.7 1000.75   563.3 1007.91   573.1  1015.5   582.9  1017.1
   592.7 1024.76   602.5 1029.61     622 1032.64   641.6  1039.7   661.2 1050.78
   710.2 1068.53   759.2 1091.08   798.3 1099.13   847.3 1114.92   935.5 1135.81
#Mann= 3 , 0 , 0
       0      .1       0   462.8    .045       0   477.8      .1       0
Bank Sta=462.8,477.8
XS Rating Curve= 0 ,0
Exp/Cntr=0.3,0.1

Type RM Length L Ch R = 1 ,9338.6  ,428.479,410.057,395.242
XS GIS Cut Line= 3
     1754637.836      356009.657     1754255.975      355772.201
       1753789.7      355627.755
#Sta/Elev= 30
       0 1131.45    68.4 1115.63    78.2 1115.33   127.1 1103.27   146.6 1092.74
   156.4 1090.43     176  1080.5   195.5 1075.35   215.1 1066.09   254.2 1052.16
   312.8 1034.29   332.4  1024.7   351.9 1018.07   400.8  989.51   420.3  984.27
   435.3  977.72   449.7  975.29   450.3  975.42   469.2  980.27   498.5  983.95
   547.3   987.6   566.8  995.48   586.3 1007.27     684 1026.46   703.5 1032.43
   752.3 1054.27   791.4 1067.16   830.4 1077.47   879.2 1096.72   937.8 1110.51
#Mann= 3 , 0 , 0
       0      .1       0   435.3    .045       0   450.3      .1       0
Bank Sta=435.3,450.3
XS Rating Curve= 0 ,0
Exp/Cntr=0.3,0.1

Type RM Length L Ch R = 1 ,8928.6  ,251.856,248.484,245.847
XS GIS Cut Line= 3
     1754676.792      355277.692     1754223.983      355390.527
     1753787.476      355514.432
#Sta/Elev= 30
       0 1116.82    48.6  1098.8    97.2 1083.96   145.8 1061.51   165.3 1054.91
   223.6 1041.01   311.1 1011.27   330.5 1000.18     350  992.29   359.7  985.55
   388.9  977.27   447.2  971.13   459.2  971.13   474.2  971.49   514.9  980.46
   572.9  980.97   592.2  983.26   640.4 1009.94   659.7 1015.68   688.7 1028.21
     708 1043.27   717.7 1046.51     737 1061.23   765.9 1071.35   785.2 1074.79
   823.9 1087.75   843.2 1091.57   862.5 1100.43   881.8 1103.25   920.4 1115.45
#Mann= 3 , 0 , 0
       0      .1       0   459.2    .045       0   474.2      .1       0
Bank Sta=459.2,474.2
XS Rating Curve= 0 ,0
Exp/Cntr=0.3,0.1

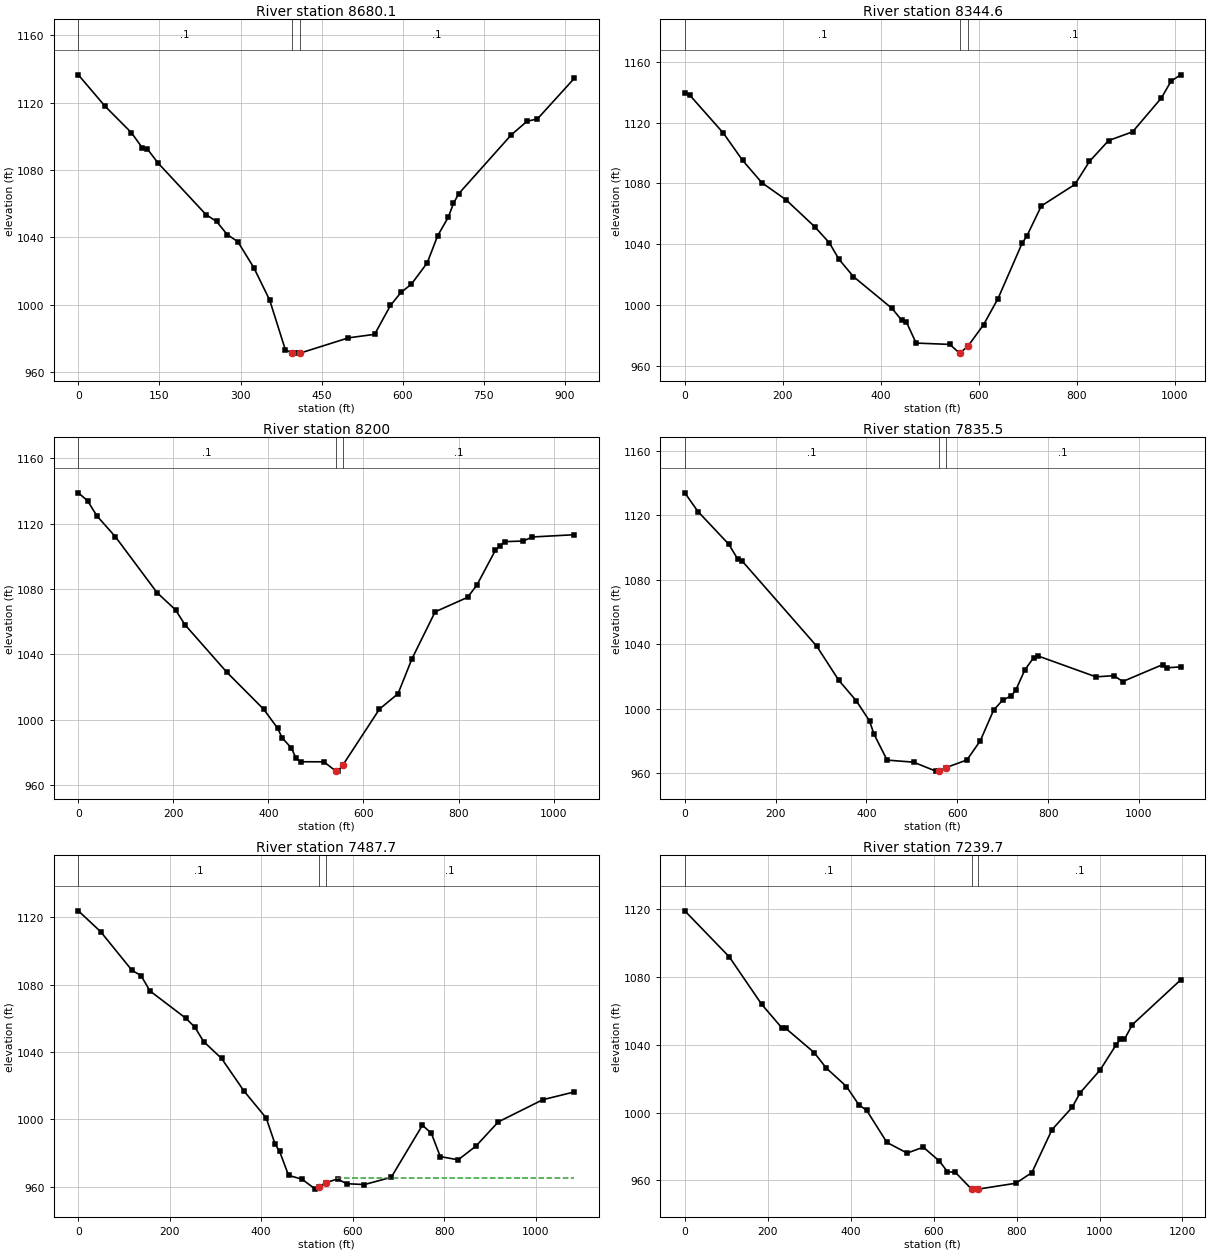
Type RM Length L Ch R = 1 ,8680.1  ,332.85,335.463,338.076
XS GIS Cut Line= 3
     1754583.794      355001.729     1754261.545      355122.341
     1753731.585      355339.583
#Sta/Elev= 30
       0 1136.53    49.2 1117.94    98.3 1102.09     118 1093.24   127.8 1092.36
   147.5 1084.08   235.9 1053.51   255.6 1049.38   275.3 1041.61   294.9 1037.36
   324.4 1021.96   353.8 1002.66   382.9     973     395  971.36   402.3  971.13
     410  971.13   499.4   980.2   547.9   982.3   577.1  999.46   596.5 1007.17
   615.9 1012.13     645 1024.71   664.4 1040.89   683.9  1051.8   693.6 1060.09
   703.3 1065.85   800.3 1100.77   829.5 1108.91   848.9 1110.33   916.8 1134.35
#Mann= 3 , 0 , 0
       0      .1       0     395    .045       0     410      .1       0
Bank Sta=395,410
XS Rating Curve= 0 ,0
Exp/Cntr=0.3,0.1

Type RM Length L Ch R = 1 ,8344.6  ,146.359,144.567,142.775
XS GIS Cut Line= 3
     1754534.268      354759.427     1753870.714      354944.105
      1753649.53      355180.322
#Sta/Elev= 30
       0 1139.35     9.8 1138.11    78.7 1113.08   118.1 1095.14   157.4  1080.5
   206.6  1069.3   265.7 1051.48   295.2 1041.03   314.9 1030.19   344.4 1018.87
   423.1  998.01   442.8  990.31   452.6  988.98   472.3  975.26   541.2  974.38
   560.9  968.66   562.9  969.05   577.9   973.1   610.1  987.35   639.6  1004.5
   688.8 1040.81   698.6 1045.62     728 1065.27   796.6 1079.39   826.1 1094.43
   865.3 1108.17   914.3  1113.9   973.2 1136.14   992.8 1147.14  1012.4 1151.31
#Mann= 3 , 0 , 0
       0      .1       0   562.9    .045       0   577.9      .1       0
Bank Sta=562.9,577.9
XS Rating Curve= 0 ,0
Exp/Cntr=0.3,0.1

Type RM Length L Ch R = 1 ,8200    ,364.817,364.59,364.363
XS GIS Cut Line= 3
      1754513.34      354689.091     1754086.215      354728.721
     1753509.375      354940.082
#Sta/Elev= 30
       0 1138.76    19.5 1133.87      39 1124.68      78 1111.92   165.7 1077.75
   204.7 1067.19   224.2 1058.19     312 1029.26     390  1006.5   419.2  994.94
     429     989   448.5   982.7   458.2  976.42     468  974.41   516.7  974.37
   541.5  968.78     546  968.68   556.5  972.34   633.7 1006.63   672.7 1015.99
     702 1037.34   750.8 1066.04     819 1074.88   838.5 1082.33   877.5 1103.61
   887.3 1106.47     897 1108.92     936  1109.3   955.5 1111.78  1043.3 1113.16
#Mann= 3 , 0 , 0
       0      .1       0   541.5    .045       0   556.5      .1       0
Bank Sta=541.5,556.5
XS Rating Curve= 0 ,0
Exp/Cntr=0.3,0.1

Type RM Length L Ch R = 1 ,7835.5  ,348.931,347.758,346.585
XS GIS Cut Line= 3
     1754372.433      354345.629      1753883.66      354416.083
     1753324.434      354627.444
#Sta/Elev= 30
       0 1133.96      29 1122.36    96.8 1102.07   116.2    1093   125.9 1091.77
   290.5  1038.8   338.9 1017.69   377.6  1004.9   406.7  992.44   416.4  984.32
   445.4  968.12   503.6  966.85   552.6  961.28   559.7  961.46   574.7  963.42
   621.2  968.21   650.6  980.11     680  999.16   699.6 1005.25   719.2 1008.07
     729  1011.7   748.6 1024.02   768.2 1031.75     778 1032.71   905.4 1019.77
   944.7 1020.52   964.3 1016.89  1052.5 1027.41  1062.3 1025.42  1091.7 1025.95
#Mann= 3 , 0 , 0
       0      .1       0   559.7    .045       0   574.7      .1       0
Bank Sta=559.7,574.7
XS Rating Curve= 0 ,0
Exp/Cntr=0.3,0.1

Type RM Length L Ch R = 1 ,7487.7  ,243.973,248.05,252.128
XS GIS Cut Line= 3
     1754314.283      354081.113     1753955.441      354032.621
      1753286.25      354304.176
#Sta/Elev= 30
       0 1123.88    48.9 1111.47   117.4  1088.5     137 1085.45   156.6  1076.3
   234.9 1060.11   254.5 1054.88     274 1046.23   313.2 1036.19   362.1  1016.9
   410.9 1000.78   430.4  985.19   440.2  980.93   459.7  966.76     489  964.46
   518.3  958.56   525.7  959.61   540.7  962.37     567  964.57   586.6  961.78
   625.6  961.28   684.2  965.56   752.5  996.54     772  991.72   791.5   977.9
   830.6  975.97   869.6  984.14   918.4   998.5    1016  1011.7  1084.3 1016.27
#Mann= 3 , 0 , 0
       0      .1       0   525.7    .045       0   540.7      .1       0
#XS Ineff= 2 , 0
                          565.46          965.13
Permanent Ineff=
       F       F
Bank Sta=525.7,540.7
XS Rating Curve= 0 ,0
Exp/Cntr=0.3,0.1

Type RM Length L Ch R = 1 ,7239.7  ,306.485,304.705,302.925
XS GIS Cut Line= 3
      1754391.87      353538.001     1753892.467      353823.247
     1753289.207      353968.558
#Sta/Elev= 30
       0 1119.19   107.2    1092   185.2 1063.99   233.9 1050.06   243.7 1049.67
   311.9 1035.44   341.2 1026.26   389.9 1015.37   419.2 1004.73   438.7  1001.2
   487.4  982.31   536.1  976.01   575.1  979.51   613.9  971.29   633.3  965.02
   652.7  964.57   691.5  954.72   692.2  954.72   707.2  954.72   798.1  958.19
   836.9  964.48   885.4  989.84   933.9 1003.01   953.3 1011.66  1001.7 1025.19
  1040.5 1040.17  1050.2 1043.19  1059.9 1043.21  1079.3 1051.94  1195.6 1078.34
#Mann= 3 , 0 , 0
       0      .1       0   692.2    .045       0   707.2      .1       0
Bank Sta=692.2,707.2
XS Rating Curve= 0 ,0
Exp/Cntr=0.3,0.1

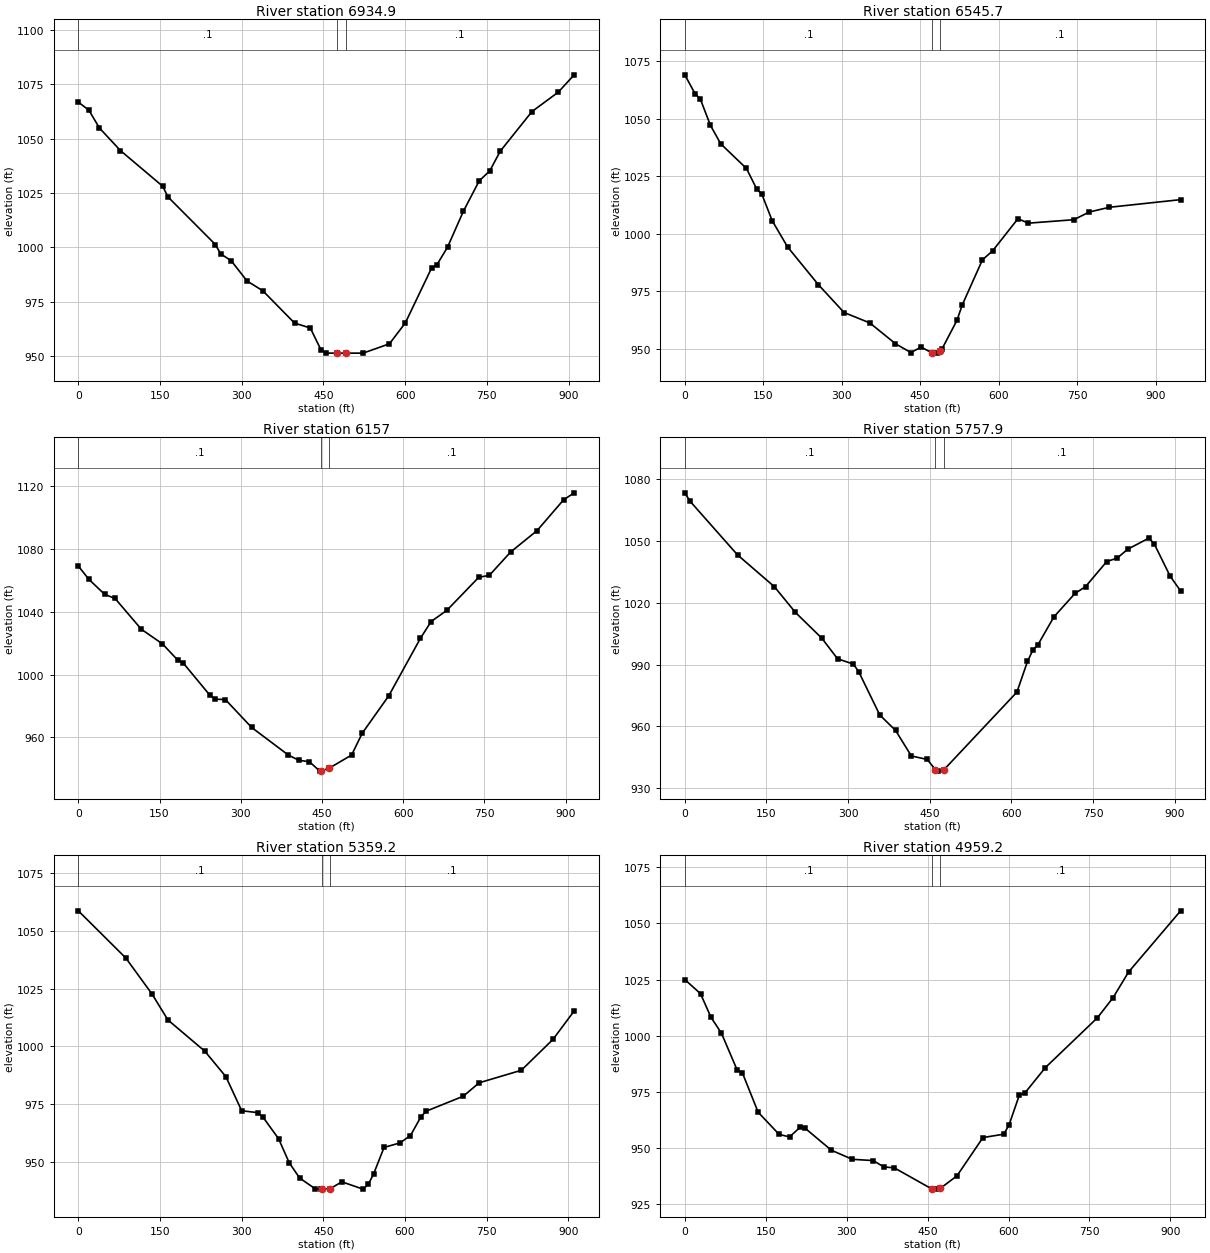
Type RM Length L Ch R = 1 ,6934.9  ,384.572,389.197,393.847
XS GIS Cut Line= 3
     1754140.409      353431.063     1753702.976      353556.044
     1753269.904      353696.748
#Sta/Elev= 30
       0 1066.74    19.4 1063.02    38.7 1054.85    77.4 1044.46   154.9 1028.09
   164.6 1023.18   251.7 1001.29   261.3  997.04   280.7  993.88   309.7  984.58
   338.8  980.06   396.9  965.25   425.9  962.98   445.3  953.03   454.9  951.44
   475.7  951.44   490.7  951.44   522.8  951.44   571.2  955.73   600.3   965.3
   648.7  990.61   658.4  992.07   677.8 1000.09   706.8 1016.54   735.9 1030.54
   755.3 1035.14   774.7 1044.22   832.8 1062.39   881.2 1071.32   910.3 1079.27
#Mann= 3 , 0 , 0
       0      .1       0   475.7    .045       0   490.7      .1       0
Bank Sta=475.7,490.7
XS Rating Curve= 0 ,0
Exp/Cntr=0.3,0.1

Type RM Length L Ch R = 1 ,6545.7  ,375.901,388.767,402.521
XS GIS Cut Line= 3
     1754022.237      353147.842     1753524.283       353203.14
     1753079.337      353244.669
#Sta/Elev= 30
       0 1068.99    19.6  1060.8    29.5 1058.58    49.1 1047.01    68.8 1039.01
   117.9 1028.33   137.5  1019.4   147.4 1017.12     167 1005.68   196.5  994.26
   255.4  977.87   304.5  965.79   353.7  961.28   402.8  952.23   432.2  948.42
   451.9  950.78   472.2  948.29   481.4  948.16   487.2   949.1   491.2  949.75
   520.4  962.44   530.2  968.96     569  988.67   588.4  992.55     637 1006.54
   656.5 1004.58   743.9 1006.09     773 1009.41   811.9 1011.49   947.9  1014.8
#Mann= 3 , 0 , 0
       0      .1       0   472.2    .045       0   487.2      .1       0
Bank Sta=472.2,487.2
XS Rating Curve= 0 ,0
Exp/Cntr=0.3,0.1

Type RM Length L Ch R = 1 ,6157    ,390.973,399.094,405.749
XS GIS Cut Line= 3
     1754047.856        353039.2     1753638.468      352838.935
     1753233.607      352620.666
#Sta/Elev= 30
       0 1069.18    19.4 1060.74    48.5 1051.17    67.9 1048.49   116.4 1028.85
   155.1  1019.6   184.2 1008.97   193.9 1007.27   242.4     987   252.1  984.25
   271.5  984.04     320  966.23   387.9  948.59   407.3  945.27   426.7  944.37
     446  938.35   448.2  938.46   463.2  940.21   504.7  948.63   524.2  962.48
   573.2  986.35   631.9 1023.15   651.5 1033.78   680.8    1041   739.5 1062.02
   759.1 1063.27   798.3 1078.13   847.2 1091.81   896.1 1111.42   915.7 1115.91
#Mann= 3 , 0 , 0
       0      .1       0   448.2    .045       0   463.2      .1       0
Bank Sta=448.2,463.2
XS Rating Curve= 0 ,0
Exp/Cntr=0.3,0.1

Type RM Length L Ch R = 1 ,5757.9  ,401.378,398.656,395.321
XS GIS Cut Line= 3
     1754156.327      352852.476     1753853.761      352512.861
     1753531.836       352190.08
#Sta/Elev= 30
       0 1073.21     9.7 1069.12    96.8 1043.14   164.5 1027.72   203.2 1015.24
   251.6 1002.77   280.6  992.77   309.7   990.2   319.4  986.53   358.1  965.53
   387.1  958.05   416.1  945.68   445.2  943.98   460.4  939.03   464.5  938.32
   475.4  938.84     610  976.62   629.4  991.48   639.1   996.9   648.8  999.65
   677.9 1013.06   716.7 1024.45   736.1 1027.75   774.9 1039.87   794.3  1041.6
   813.7 1045.91   852.5 1051.26   862.2 1048.49   891.3  1032.9   910.7 1025.62
#Mann= 3 , 0 , 0
       0      .1       0   460.4    .045       0   475.4      .1       0
Bank Sta=460.4,475.4
XS Rating Curve= 0 ,0
Exp/Cntr=0.3,0.1

Type RM Length L Ch R = 1 ,5359.2  ,392.011,400,404.763
XS GIS Cut Line= 3
     1754456.305      352492.647     1754105.803      352202.726
      1753740.06      351930.819
#Sta/Elev= 30
       0 1058.56    87.1  1038.2   135.5 1022.56   164.5 1011.42   232.3  997.91
     271   986.9     300  972.18   329.1  971.38   338.7  969.55   367.8  960.09
   387.1   949.8   406.5   943.1   435.5  938.39   445.2  938.32   447.4  938.32
   462.4   938.5     484  941.48   522.7  938.32   532.4  940.35   542.1  944.78
   561.5  956.35   590.6  958.28     610  961.47   629.4  969.66   639.1  972.02
     707  978.46   736.1  984.26   813.6  989.67   871.8 1003.04   910.6  1015.3
#Mann= 3 , 0 , 0
       0      .1       0   447.4    .045       0   462.4      .1       0
Bank Sta=447.4,462.4
XS Rating Curve= 0 ,0
Exp/Cntr=0.3,0.1

Type RM Length L Ch R = 1 ,4959.2  ,399.895,400,405.556
XS GIS Cut Line= 3
     1754607.879      352313.119     1754369.969      351912.642
     1754068.203      351574.664
#Sta/Elev= 30
       0 1025.03    29.1 1018.74    48.5 1008.23    67.9 1001.15      97   984.8
   106.7  983.53   135.9     966   174.7  956.14   194.1  954.99   213.5  959.24
   223.2   958.8   271.7  949.06   310.5  945.03   349.4  944.46   368.8  941.64
   388.2  941.24   458.3  931.77   465.8  931.76   473.3  932.05   504.4  937.67
   552.6  954.72   591.1   956.2   600.8  960.26   620.1  973.68   629.7  974.38
   668.3  985.86   764.7 1008.02   793.6 1016.94   822.5  1028.4   918.9 1055.61
#Mann= 3 , 0 , 0
       0      .1       0   458.3    .045       0   473.3      .1       0
Bank Sta=458.3,473.3
XS Rating Curve= 0 ,0
Exp/Cntr=0.3,0.1

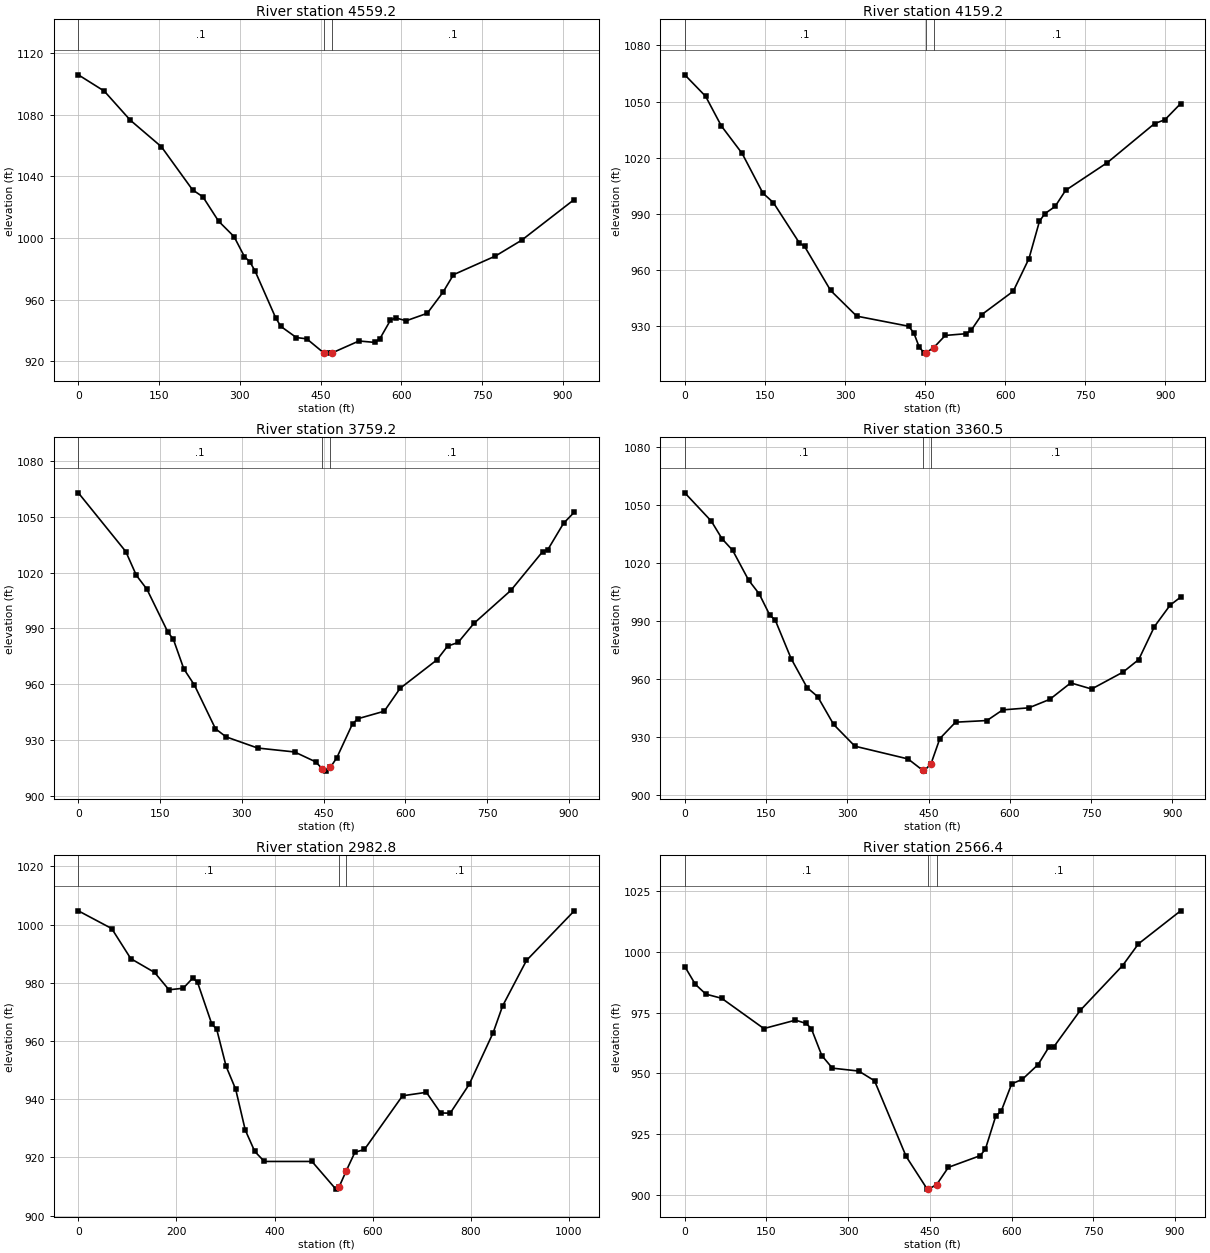
Type RM Length L Ch R = 1 ,4559.2  ,407.709,400,394.504
XS GIS Cut Line= 3
     1754919.768       352106.38     1754685.129      351707.399
     1754471.049      351302.357
#Sta/Elev= 30
       0 1105.95    48.2 1095.37    96.4 1076.53   154.3 1059.24   212.1 1031.27
   231.4  1026.7   260.4 1010.95   289.3 1000.85   308.6  987.82   318.2  984.68
   327.9  978.84   366.4  948.26   376.1  942.57     405  935.32   424.3  934.48
   455.4   925.5   462.9   925.2   470.4   925.2   521.3  933.09   550.6  932.16
   560.3  934.65   579.8  946.62   589.6  948.05   609.1  946.23   648.1  951.07
   677.3  964.73   696.8  976.13   774.8  988.27   823.5  998.54     921 1024.93
#Mann= 3 , 0 , 0
       0      .1       0   455.4    .045       0   470.4      .1       0
Bank Sta=455.4,470.4
XS Rating Curve= 0 ,0
Exp/Cntr=0.3,0.1

Type RM Length L Ch R = 1 ,4159.2  ,390.056,400,406.672
XS GIS Cut Line= 3
     1755368.827      351805.038     1755012.329      351516.868
     1754687.355      351177.154
#Sta/Elev= 30
       0  1064.3      39  1052.8    68.3 1037.01   107.3 1022.26   146.3 1000.97
   165.8  995.94   214.6   974.3   224.3  972.47   273.1  948.88   321.9  935.16
   419.4  929.74   429.1  926.02   438.9   918.6   448.6  915.36   450.9  915.51
   465.9  918.23   487.8  924.83     527  925.76   536.8   927.8   556.3  936.02
   615.1  948.49   644.5  965.97   664.1  985.86   673.9  989.92   693.5  993.86
   713.1 1002.47   791.4 1017.35   879.6 1038.19   899.1 1040.26   928.5  1048.9
#Mann= 3 , 0 , 0
       0      .1       0   450.9    .045       0   465.9      .1       0
Bank Sta=450.9,465.9
XS Rating Curve= 0 ,0
Exp/Cntr=0.3,0.1

Type RM Length L Ch R = 1 ,3759.2  ,391.732,398.756,406.047
XS GIS Cut Line= 3
     1755528.105      351698.187     1755328.622      351289.248
      1755129.14      350880.308
#Sta/Elev= 30
       0 1062.82    87.1 1031.29   106.5 1018.52   125.9 1011.07   164.6  987.89
   174.3  984.28   193.6  968.31     213  959.64   251.7  936.17   271.1  931.82
   329.1  925.82   396.9  923.71   435.6   918.4   447.5  914.73     455  913.42
   462.5  915.41   474.4  920.61   503.4  938.93   513.1  941.55   561.5  945.59
   590.5  957.85   658.3  973.18   677.7  980.54     697  982.48   726.1  992.76
   793.8 1010.44   851.9 1031.16   861.6 1032.28   890.6  1046.5     910 1052.35
#Mann= 3 , 0 , 0
       0      .1       0   447.5    .045       0   462.5      .1       0
Bank Sta=447.5,462.5
XS Rating Curve= 0 ,0
Exp/Cntr=0.3,0.1

Type RM Length L Ch R = 1 ,3360.5  ,385.865,377.668,369.205
XS GIS Cut Line= 3
     1755751.544       351588.28     1755685.643      351131.955
      1755634.39      350680.927
#Sta/Elev= 30
       0  1056.4      49 1041.72    68.7 1032.62    88.3 1026.63   117.7 1011.23
   137.3 1004.08     157  992.99   166.8  990.58   196.2  970.58   225.6  955.58
   245.2  950.89   274.7  936.46   313.9  925.23     412  918.63   439.5  912.65
   441.4  912.32   454.5  916.25   470.7  929.18   499.7  937.66   557.6  938.51
   586.6  944.02   634.9  945.09   673.5  949.47   712.2     958   750.8  954.83
   808.8   963.6   837.7  970.08   866.7  987.17   895.7  998.27     915 1002.39
#Mann= 3 , 0 , 0
       0      .1       0   439.5    .045       0   454.5      .1       0
Bank Sta=439.5,454.5
XS Rating Curve= 0 ,0
Exp/Cntr=0.3,0.1

Type RM Length L Ch R = 1 ,2982.8  ,433.545,416.359,400.231
XS GIS Cut Line= 3
     1756226.247       351567.11     1756085.339      351122.371
     1755821.138      350646.809
#Sta/Elev= 30
       0 1004.76      68  998.67   106.9  988.33   155.5  983.57   184.7  977.63
   213.8  978.15   233.3  981.66     243  980.17   272.1   965.8   281.9  964.13
   301.3  951.28   320.7  943.45   340.2  929.44   359.6  922.07   379.1  918.63
   476.2  918.63   524.8  909.12   531.1  909.73   546.1  915.42   563.7  921.78
   583.1  922.74   660.8   941.2   709.4  942.39   738.5  935.29     758  935.23
   796.8  945.17   845.4  962.84   864.8  972.09   913.4   987.7  1010.6 1004.72
#Mann= 3 , 0 , 0
       0      .1       0   531.1    .045       0   546.1      .1       0
Bank Sta=531.1,546.1
XS Rating Curve= 0 ,0
Exp/Cntr=0.3,0.1

Type RM Length L Ch R = 1 ,2566.4  ,387.803,399.801,407.623
XS GIS Cut Line= 3
     1756677.391       350854.52     1756244.847      350713.692
     1755818.726      350552.439
#Sta/Elev= 30
       0  994.02    19.4  986.69    38.7  982.65    67.7  980.94   145.2  968.45
   203.2  971.92   222.6  970.58   232.3  968.47   251.6  957.32     271  952.12
   319.4  950.93   348.4  946.92   406.5  915.69   445.2  902.23   447.4  902.23
   462.4  904.07     484  911.22   542.1     916   551.8  918.59   571.2  932.48
   580.9  934.32   600.3  945.66   619.7  947.49   648.8  953.61   668.2  960.67
   677.9     961   726.3  975.99   803.9  994.42     833 1003.39   910.5 1017.01
#Mann= 3 , 0 , 0
       0      .1       0   447.4    .045       0   462.4      .1       0
Bank Sta=447.4,462.4
XS Rating Curve= 0 ,0
Exp/Cntr=0.3,0.1

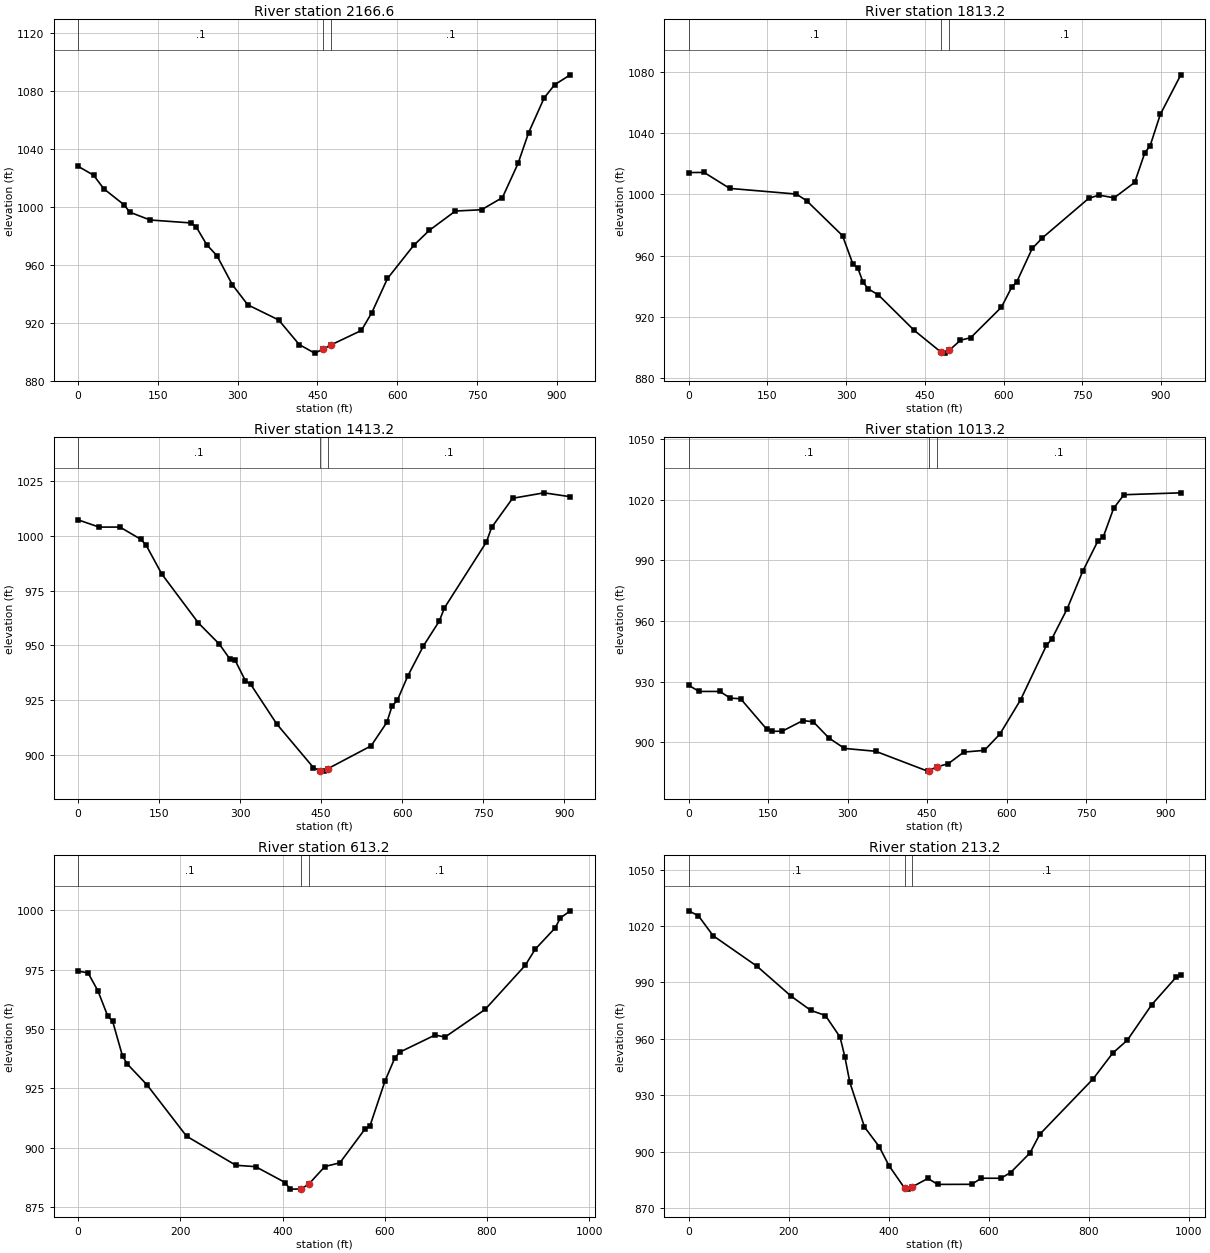
Type RM Length L Ch R = 1 ,2166.6  ,375.982,353.398,342.148
XS GIS Cut Line= 3
     1756751.275      350720.142     1756436.477      350366.277
     1756080.241      350088.534
#Sta/Elev= 30
       0 1027.85      29 1021.73    48.3 1012.33      87 1001.13    96.7  996.29
   135.3  990.85   212.6  988.81   222.3  985.89   241.6  973.91     261   966.2
     290  946.19     319  932.37     377  921.95   415.6  905.02   444.6  899.09
   460.5  901.73   475.5  904.77   532.5  914.71   552.2  927.01   581.6  950.53
   630.7  973.28   660.2   983.7   709.3  997.03   758.4  997.91   797.7 1006.29
   827.1 1029.83   846.8 1050.88   876.2    1075   895.9  1084.1   925.3 1090.91
#Mann= 3 , 0 , 0
       0      .1       0   460.5    .045       0   475.5      .1       0
Bank Sta=460.5,475.5
XS Rating Curve= 0 ,0
Exp/Cntr=0.3,0.1

Type RM Length L Ch R = 1 ,1813.2  ,392.878,400,397.481
XS GIS Cut Line= 3
     1757077.452      350060.728     1756590.461      350101.002
     1756160.214      349972.237
#Sta/Elev= 30
       0 1014.29    29.3  1014.4    78.2 1003.94   205.2 1000.23   224.8  995.88
   293.2  973.01   312.7   954.7   322.5  951.66   332.3  942.57   342.1  938.27
   361.6  934.24     430  911.02   481.2  896.75   488.7   896.2   496.2  897.93
   517.9  904.63   537.5  906.32     596  926.25   615.6  939.34   625.3  942.87
   654.6  964.64   674.2  971.62     762  997.34   781.5  999.54   810.8  997.78
   849.9 1007.85   869.4 1027.39   879.2 1031.68   898.7  1052.3   937.8 1078.22
#Mann= 3 , 0 , 0
       0      .1       0   481.2    .045       0   496.2      .1       0
Bank Sta=481.2,496.2
XS Rating Curve= 0 ,0
Exp/Cntr=0.3,0.1

Type RM Length L Ch R = 1 ,1413.2  ,418.249,400,387.29
XS GIS Cut Line= 3
      1757099.03      349813.677     1756655.188      349713.511
      1756206.63       349630.33
#Sta/Elev= 30
       0 1007.22    38.7 1003.93    77.4 1003.93   116.2  998.33   125.9  995.65
   154.9  982.51   222.7  960.19   261.4  950.56   280.7  943.85   290.4  943.29
   309.8   933.8   319.5   932.2   367.9  914.07   435.6  894.25   447.5  892.83
     455  892.63   462.5  893.76   542.4  904.15   571.5  914.85   581.2  922.29
   590.9  924.92   610.3  936.01   639.4  949.78   668.5     961   678.3  967.11
   755.9  997.12   765.6 1003.79   804.4 1017.06   862.7 1019.55   911.2 1017.77
#Mann= 3 , 0 , 0
       0      .1       0   447.5    .045       0   462.5      .1       0
Bank Sta=447.5,462.5
XS Rating Curve= 0 ,0
Exp/Cntr=0.3,0.1

Type RM Length L Ch R = 1 ,1013.2  ,389.13,400,393.588
XS GIS Cut Line= 3
     1757015.651      349087.236     1756630.908       349340.06
      1756198.48      349518.758
#Sta/Elev= 30
       0  928.24    19.6   925.2    58.8   925.2    78.4  921.91      98  921.59
   146.9  906.65   156.7  905.51   176.3  905.55   215.5  910.82   235.1   910.2
   264.5  902.22   293.9  897.05   352.6  895.65   450.6  885.84   452.9  886.04
   467.9  887.94   489.6  889.48   518.9  895.24   557.9   896.1   587.1  904.17
   626.1  921.07   674.8  947.92   684.6  950.98   713.8  965.94   743.1  984.45
   772.3  999.74   782.1 1001.57   801.6 1015.67     821 1022.37   928.3 1023.31
#Mann= 3 , 0 , 0
       0      .1       0   452.9    .045       0   467.9      .1       0
Bank Sta=452.9,467.9
XS Rating Curve= 0 ,0
Exp/Cntr=0.3,0.1

Type RM Length L Ch R = 1 ,613.2   ,429.947,400,390.939
XS GIS Cut Line= 3
     1756971.027      348919.591     1756529.616      348963.066
     1756102.517       349258.51
#Sta/Elev= 30
       0  974.41    19.3  973.68    38.6  966.13    57.9  955.48    67.5  953.27
    86.8  938.61    96.4  935.22     135  926.41   212.1  904.85   308.6  892.59
   347.1  892.02     405  885.33   414.6  882.54     436  882.58     451   884.6
   482.7  892.06   512.1  893.63   561.1  907.83   570.9  909.14   600.3  928.04
   619.9  937.97   629.7  940.31   698.3  947.47   717.9  946.63   796.3  958.27
   874.7  976.83   894.3  983.64   933.5  992.65   943.3  996.78   962.9  999.82
#Mann= 3 , 0 , 0
       0      .1       0     436    .045       0     451      .1       0
Bank Sta=436,451
XS Rating Curve= 0 ,0
Exp/Cntr=0.3,0.1

Type RM Length L Ch R = 1 ,213.2   ,218.526,213.249,205.994
XS GIS Cut Line= 3
     1756359.257      348278.684     1756294.726      348713.151
     1756033.842      349190.907
#Sta/Elev= 30
       0 1028.07    19.5 1025.44    48.8 1014.85   136.7  998.56     205  982.62
     244  975.14   273.3  972.39   302.6  960.91   312.3  950.22   322.1  936.84
   351.4  913.07   380.7  902.68   400.2   892.6   431.7  880.51   439.2  880.04
   446.7   881.2   478.1  885.75   497.6  882.55   565.6   882.6     585  885.83
   623.9  885.83   643.4  888.84   682.2  899.29   701.7  909.21   808.6  938.76
   847.5  952.39   876.7  959.25   925.3  978.08   973.9  992.66   983.6  994.06
#Mann= 3 , 0 , 0
       0      .1       0   431.7    .045       0   446.7      .1       0
Bank Sta=431.7,446.7
XS Rating Curve= 0 ,0
Exp/Cntr=0.3,0.1

Chan Stop Cuts=-1
Use User Specified Reach Order=0